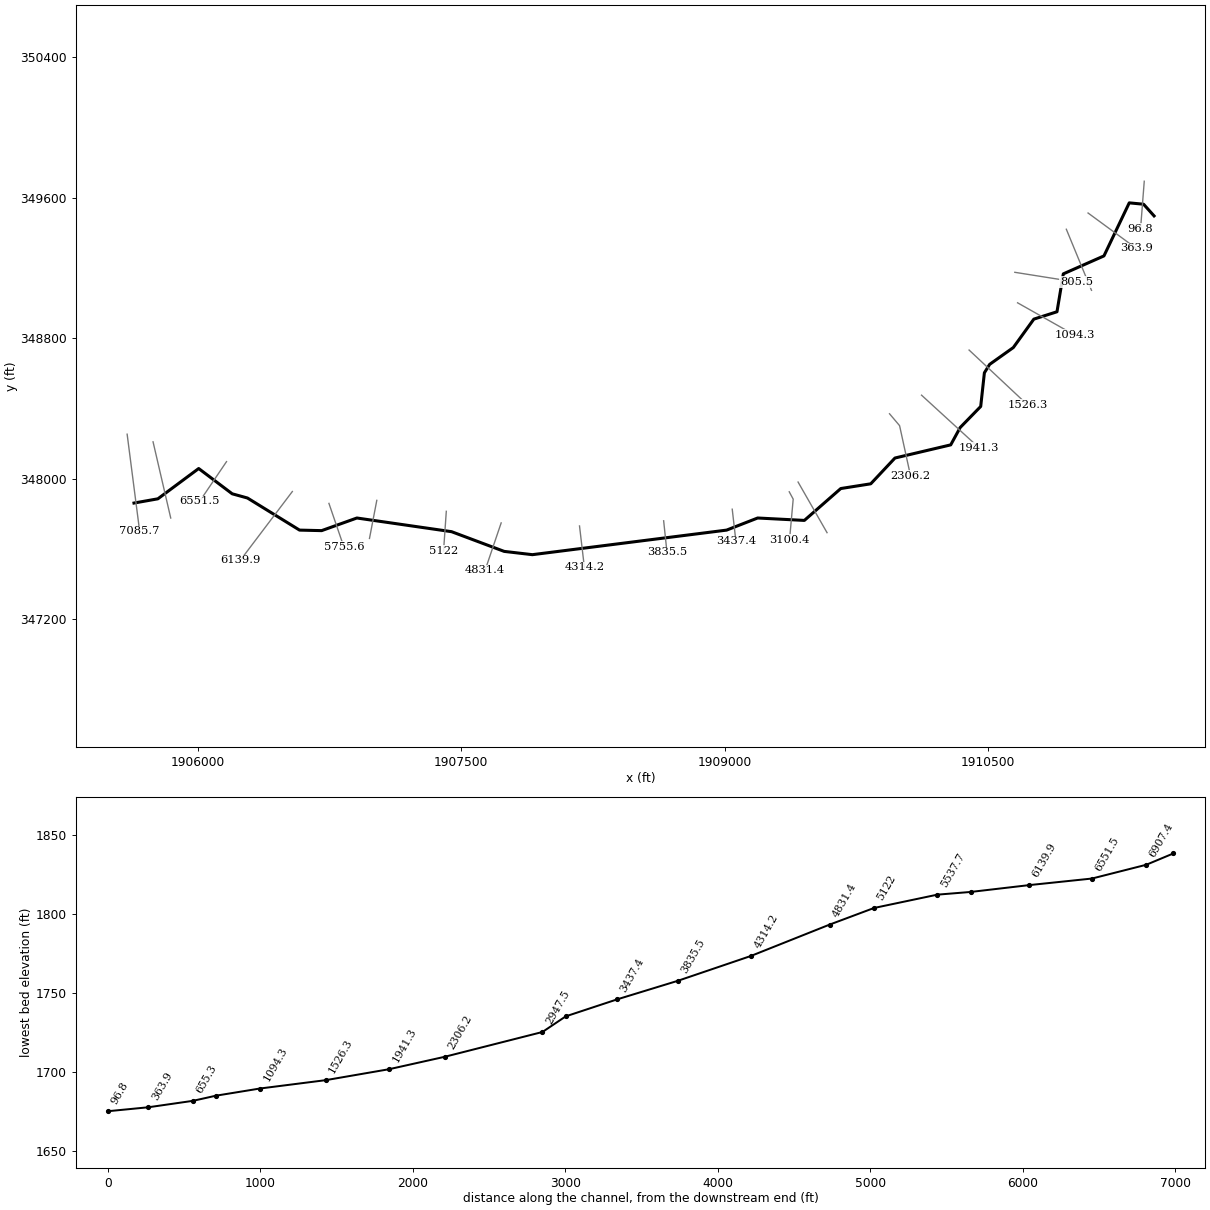
--- CHURCHCK.prj (project) ---

Proj Title=CHURCHCK
Current Plan=p01
Default Exp/Contr=0,0
English Units
Geom File=g01
Flow File=f01
Plan File=p01
BEGIN DESCRIPTION:
END DESCRIPTION:
DSS Export Rating Curves= 0
DSS Export Rating Curve Sorted= 0
DSS Export Volume Flow Curves= 0
DXF OffsetX= 0
DXF OffsetY= 0
DXF ScaleX= 0
DXF ScaleY= 0

--- CHURCHCK.p01 (plan) ---

Plan Title=Floodplain
Program Version=4.00
Geom File=g01
Flow File=f01
K Sum by GR=0
Std Step Tol=0.01
Critical Tol=0.01
Num of Std Step Trials=20
Max Error Tol=0.3
Flow Tol Ratio=0.001
Split Flow NTrial=30
Split Flow Tol=0.02
Split Flow Ratio=0.02
Log Output Level=0
Friction Slope Method=1
Unsteady Friction Slope Method=2
Unsteady Bridges Friction Slope Method=1
Global Log Level=0
CheckData=False
Run HTab=0
Run UNet=0
Run PostProcess=0
UNET Theta=0
UNET Theta Warmup=0
UNET ZTol=0
UNET ZSATol=0
UNET MxIter=0
UNET MaxInSteps=0
UNET DtIC=0
UNET DtMin=0
UNET MaxCRTS=0
UNET WFStab=0
UNET SFStab=0
UNET WFX=0
UNET SFX=0
UNET DSS MLevel=0
UNET DZMax Abort=0
UNET Convert EG Bridges=0
UNET Use Existing IB Tables=0
UNET Froude Limit=0
UNET Froude Power=0
Write IC File=0
Echo Input=False
Echo Output=False
Write Detailed=0

--- CHURCHCK.f01 (steady flow) ---

Flow Title=NFF Regression Equation
Program Version=4.10
Number of Profiles= 1
Profile Names=P100yr
River Rch & RM=CHURCHCK,Main            ,7085.7
664.5731
River Rch & RM=CHURCHCK,Main            ,3437.4
725.2603
River Rch & RM=CHURCHCK,Main            ,363.9
777.1457
Boundary for River Rch & Prof#=CHURCHCK,Main            , 1
Up Type= 0
Dn Type= 1
Dn Known WS=1679.593
DSS Import GetInterval= 0
DSS Import GetPeak= 0
DSS Import FillOption= 0

--- CHURCHCK.g01 (geometry) ---

Geom Title=USGS 10m DEM
Program Version=4.10

River Reach=CHURCHCK        ,Main
Reach XY= 30
     1905635.877       347860.45     1905771.926      347884.587
     1906004.366      348057.065     1906195.256      347913.113
     1906282.144      347889.144     1906578.763      347706.379
     1906704.601      347703.383     1906905.343       347775.29
      1907444.65      347697.391     1907744.123       347585.19
     1907904.763      347566.492     1909011.036      347706.379
     1909187.808       347775.29     1909453.846      347761.577
       1909661.2      347943.075      1909831.98       347970.04
     1909969.803      348116.851     1910287.395      348191.755
     1910341.326      348290.628     1910458.175      348410.474
     1910479.148      348602.227      1910509.11      348650.166
     1910643.936      348746.042     1910760.786      348907.834
     1910892.617       348949.78      1910928.57      349165.503
     1911160.096      349267.829     1911304.196      349569.948
     1911385.793      349562.136     1911445.512      349495.607

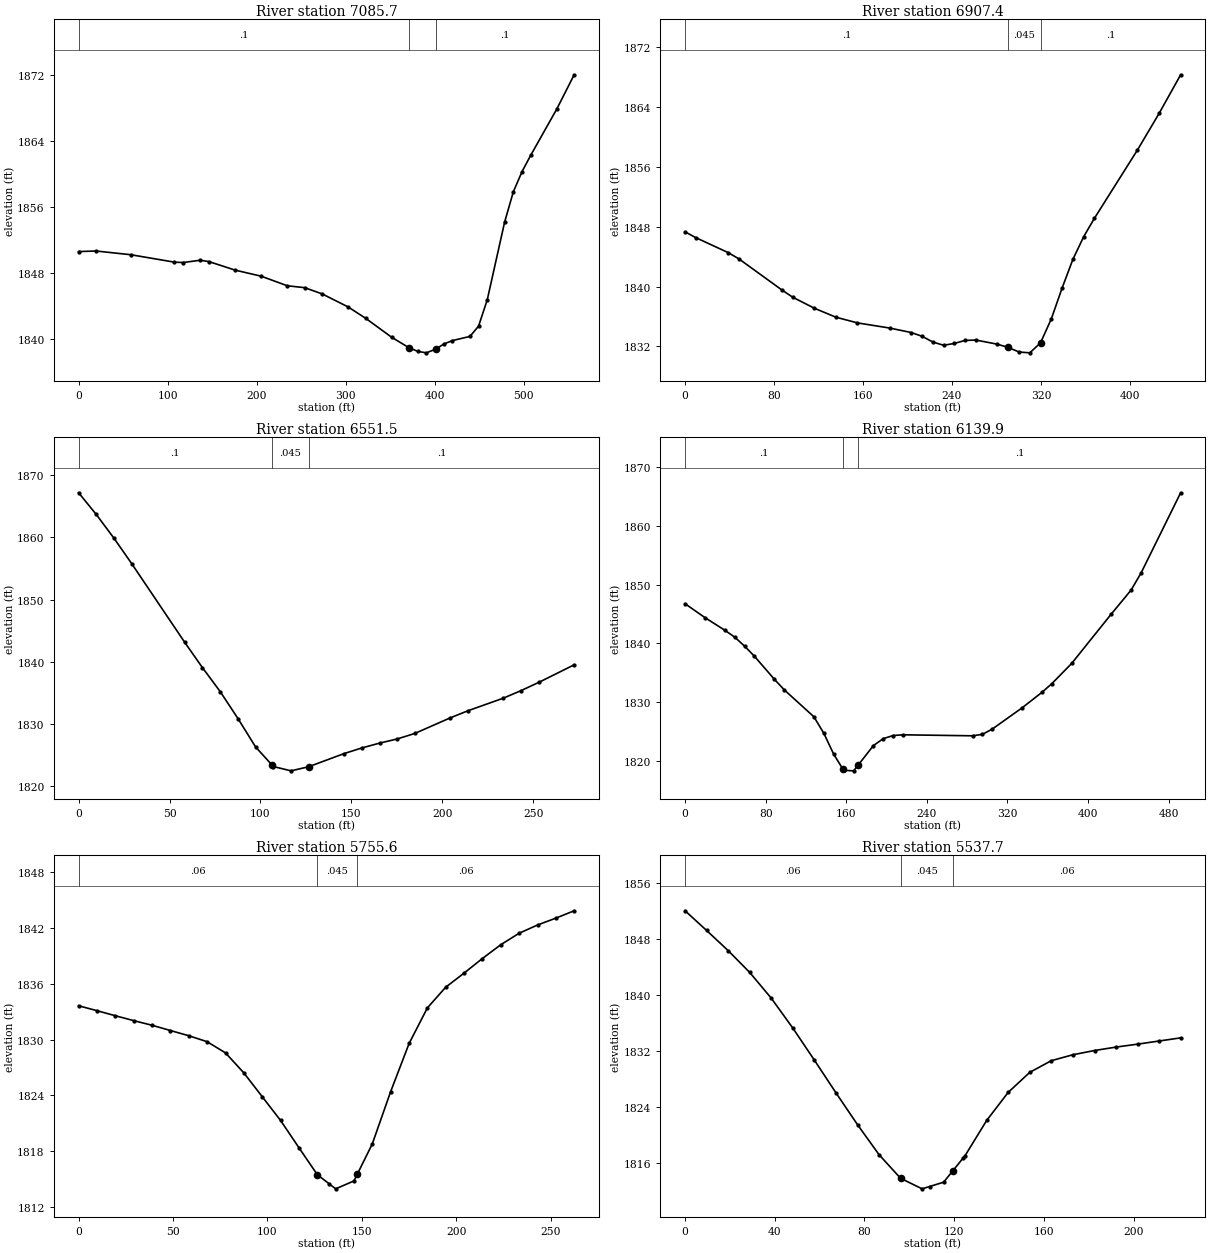
Type RM Length L Ch R = 1 ,7085.7  ,176.4,178.3,194.9
XS GIS Cut Line= 2
     1905596.867      348252.587     1905668.048      347700.503
#Sta/Elev= 30
       0 1850.61    19.5 1850.68    58.6 1850.23   107.4 1849.33   117.2 1849.28
   136.7 1849.56   146.5 1849.39   175.8 1848.36   205.1 1847.62   234.4 1846.46
   253.9 1846.23   273.4 1845.48   302.7 1843.89   322.3 1842.52   351.6 1840.21
   371.1 1838.94   380.9  1838.5   390.6 1838.32   401.3 1838.78   410.2 1839.39
   419.9 1839.81   439.5 1840.31   449.2 1841.56     459 1844.77   478.5  1854.2
   488.3 1857.88   498.1 1860.33   507.8  1862.3   537.1 1867.92   556.6 1872.07
#Mann= 3 , 0 , 0
       0      .1       0   371.1    .045       0   401.3      .1       0
Bank Sta=371.1,401.3
XS Rating Curve= 0 ,0
Exp/Cntr=0.3,0.1

Type RM Length L Ch R = 1 ,6907.4  ,374.8,356,337.1
XS GIS Cut Line= 2
     1905744.436      348209.184     1905845.131      347775.156
#Sta/Elev= 30
       0  1847.3     9.7 1846.52    38.7 1844.53    48.4 1843.69    87.2 1839.52
    96.9 1838.56   116.2  1837.1   135.6  1835.9     155 1835.14     184 1834.45
   203.4 1833.85   213.1 1833.35   222.8 1832.58   232.5 1832.15   242.2  1832.4
   251.8  1832.8   261.5 1832.85   280.9 1832.29   290.6 1831.86   300.3 1831.25
     310 1831.14   319.6 1832.48   329.3 1835.67     339 1839.79   348.7 1843.62
   358.4 1846.65   368.1 1849.12   406.8 1858.24   426.2 1863.11   445.6 1868.28
#Mann= 3 , 0 , 0
       0      .1       0   290.6    .045       0   319.6      .1       0
Bank Sta=290.6,319.6
XS Rating Curve= 0 ,0
Exp/Cntr=0.3,0.1

Type RM Length L Ch R = 1 ,6551.5  ,412.8,411.6,409.1
XS GIS Cut Line= 2
     1906162.839      348096.337     1906010.061      347870.642
#Sta/Elev= 24
       0 1867.18     9.7 1863.69    19.5 1859.84    29.2 1855.77    58.4 1843.09
    68.1 1839.04    77.9 1835.17    87.6 1830.86    97.3 1826.29   106.2 1823.42
   107.1 1823.13   116.8 1822.44   126.5  1823.1     146 1825.22   155.7 1826.12
   165.5  1826.9   175.2 1827.57   184.9 1828.46   204.4 1830.97   214.1 1832.11
   233.6 1834.14   243.3 1835.35   253.1 1836.68   272.5  1839.5
#Mann= 3 , 0 , 0
       0      .1       0   106.2    .045       0   126.5      .1       0
Bank Sta=106.2,126.5
XS Rating Curve= 0 ,0
Exp/Cntr=0.3,0.1

Type RM Length L Ch R = 1 ,6139.9  ,361.8,384.3,407.4
XS GIS Cut Line= 2
     1906537.839      347926.198     1906240.964      347533.837
#Sta/Elev= 30
       0 1846.76    19.7  1844.4    39.4 1842.25    49.2 1841.08      59 1839.55
    68.9  1837.8    88.6  1833.9    98.4  1832.1   127.9  1827.5   137.8 1824.67
   147.6  1821.1   156.8 1818.55   157.4 1818.38   167.3 1818.29   171.8 1819.26
     187  1822.6   196.8 1823.78   206.6 1824.31   216.5 1824.43   285.4 1824.26
   295.2 1824.51     305 1825.41   334.6 1829.03   354.2 1831.65   364.1 1833.14
   383.8 1836.59   423.1    1845   442.8 1849.09   452.7    1852     492 1865.67
#Mann= 3 , 0 , 0
       0      .1       0   156.8    .045       0   171.8      .1       0
Bank Sta=156.8,171.8
XS Rating Curve= 0 ,0
Exp/Cntr=0.3,0.1

Type RM Length L Ch R = 1 ,5755.6  ,229,217.9,204.9
XS GIS Cut Line= 2
     1906746.173       347858.49     1906831.242      347610.226
#Sta/Elev= 30
       0 1833.64     9.7 1833.11    19.4 1832.57    29.2 1832.04    38.9 1831.54
    48.6 1830.98    58.3 1830.42      68 1829.78    77.8 1828.57    87.5 1826.42
    97.2 1823.87   106.9 1821.32   116.6  1818.4   126.4 1815.48   132.6 1814.51
   136.1 1813.96   145.8 1814.81   147.6 1815.55   155.5 1818.79   165.2  1824.4
     175 1829.59   184.7 1833.42   194.4 1835.64   204.1 1837.15   213.8 1838.72
   223.6 1840.21   233.3 1841.44     243 1842.32   252.7 1843.06   262.4 1843.85
#Mann= 3 , 0 , 0
       0     .06       0   126.4    .045       0   147.6     .06       0
Bank Sta=126.4,147.6
XS Rating Curve= 0 ,0
Exp/Cntr=0.3,0.1

Type RM Length L Ch R = 1 ,5537.7  ,413,415.7,418.5
XS GIS Cut Line= 2
     1907018.742      347875.851     1906977.075      347658.837
#Sta/Elev= 27
       0 1852.06     9.6 1849.24    19.2 1846.36    28.8 1843.24    38.4 1839.56
      48 1835.29    57.6 1830.71    67.2 1826.04    76.9 1821.44    86.5 1817.15
    96.1 1813.77   105.7 1812.26     109 1812.59   115.3 1813.21  119.371814.829
     124 1816.67   124.9 1817.03   134.5 1822.05   144.1 1826.07   153.7 1828.93
   163.3  1830.6   172.9 1831.45   182.6 1832.06   192.2 1832.55   201.8 1832.97
   211.4 1833.42     221 1833.87
#Mann= 3 , 0 , 0
       0     .06       0    96.1    .045       0  119.37     .06       0
Bank Sta=96.1,119.37
XS Rating Curve= 0 ,0
Exp/Cntr=0.3,0.1

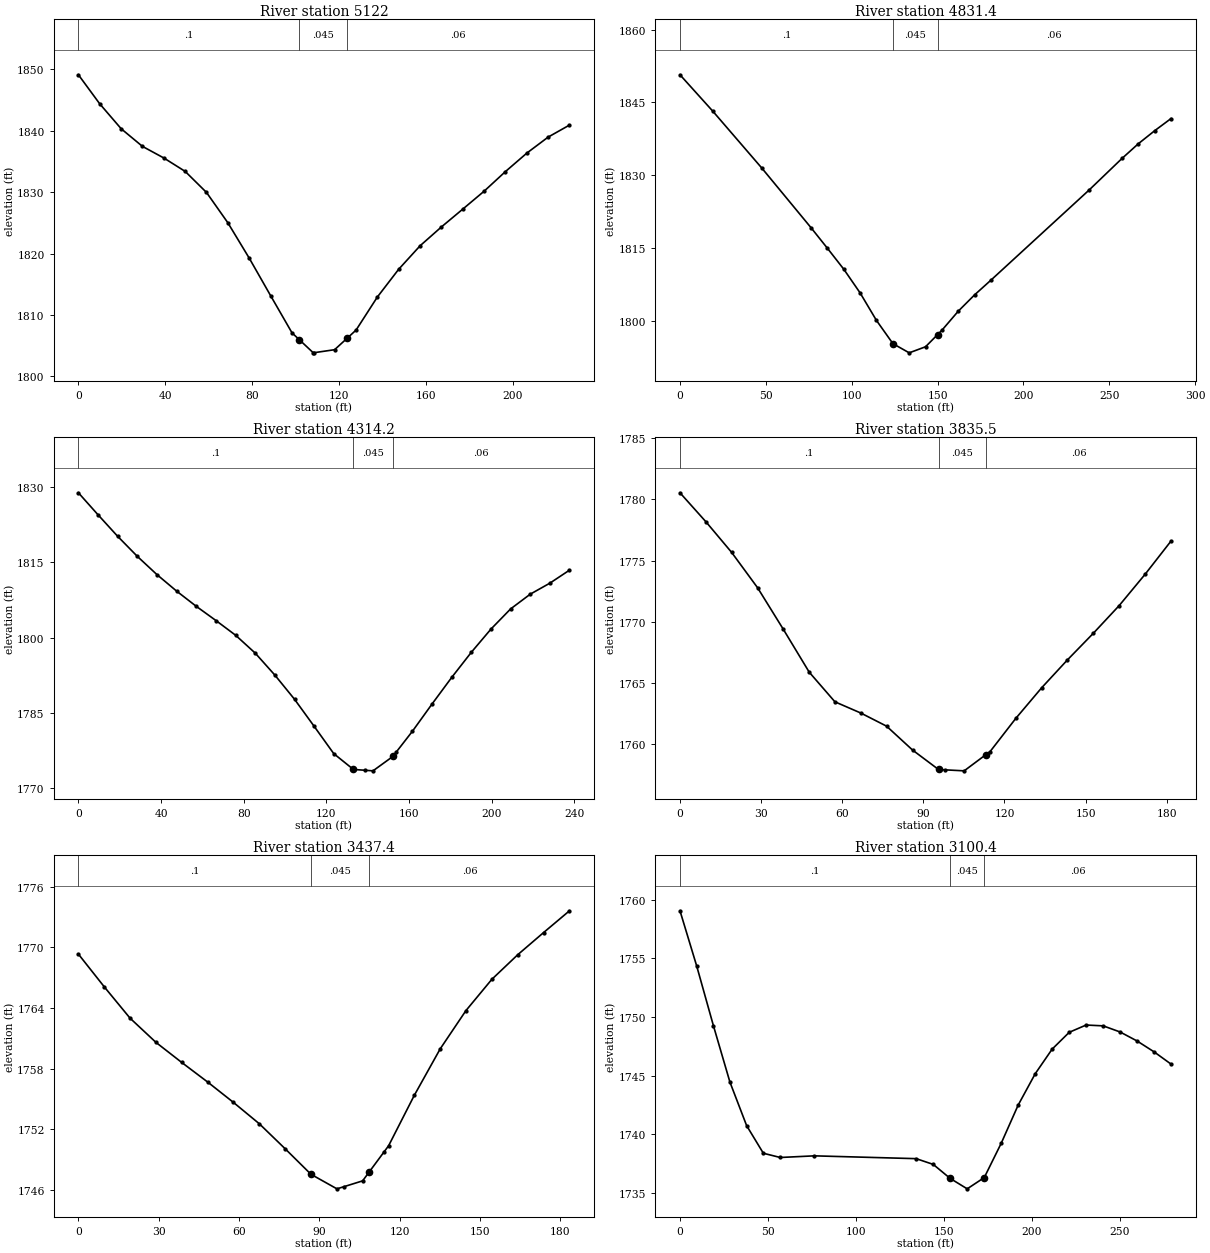
Type RM Length L Ch R = 1 ,5122    ,296.4,290.6,284.8
XS GIS Cut Line= 2
     1907414.575      347813.351      1907398.95      347587.656
#Sta/Elev= 27
       0 1849.11     9.8 1844.39    19.7 1840.32    29.5 1837.45    39.4 1835.55
    49.2 1833.37      59 1829.95    68.8 1825.03    78.7 1819.24    88.5 1813.16
    98.4 1807.08  101.761805.966   108.2 1803.83   108.7 1803.86     118 1804.34
   123.7 1806.18   127.9 1807.54   137.7 1812.92   147.5 1817.43   157.4 1821.27
   167.2 1824.33     177 1827.22   186.9 1830.16   196.7 1833.35   206.6 1836.37
   216.4 1838.97   226.2 1840.92
#Mann= 3 , 0 , 0
       0      .1       0  101.76    .045       0   123.7     .06       0
Bank Sta=101.76,123.7
XS Rating Curve= 0 ,0
Exp/Cntr=0.3,0.1

Type RM Length L Ch R = 1 ,4831.4  ,506.9,517.1,527.2
XS GIS Cut Line= 2
     1907727.075      347747.378     1907635.061      347476.545
#Sta/Elev= 21
       0 1850.68    19.1 1843.18    47.7 1831.43    76.3 1819.16    85.8 1814.94
    95.4 1810.59   104.9 1805.71   114.4 1800.05     124 1795.25   133.5 1793.35
     143  1794.6     150  1797.1   152.6 1798.03   162.1 1801.95   171.6 1805.31
   181.2 1808.37   238.4 1826.96   257.4 1833.42     267 1836.48   276.5 1839.16
     286 1841.66
#Mann= 3 , 0 , 0
       0      .1       0     124    .045       0     150     .06       0
Bank Sta=124,150
XS Rating Curve= 0 ,0
Exp/Cntr=0.3,0.1

Type RM Length L Ch R = 1 ,4314.2  ,479,478.8,478.5
XS GIS Cut Line= 2
     1908173.256      347730.017     1908201.034      347493.906
#Sta/Elev= 28
       0 1828.81     9.5 1824.43      19 1820.15    28.5 1816.17      38 1812.54
    47.6 1809.23    57.1 1806.21    66.6 1803.39    76.1 1800.47    85.6 1796.91
    95.1 1792.54   104.6 1787.74   114.1 1782.36   123.6 1776.92   133.1 1773.78
   138.8 1773.61   142.6  1773.5   152.2 1776.36   153.8 1777.21   161.7 1781.39
   171.2 1786.81   180.7 1792.09   190.2 1797.09   199.7  1801.7   209.2 1805.71
   218.7 1808.64   228.2 1810.83   237.7 1813.42
#Mann= 3 , 0 , 0
       0      .1       0   133.1    .045       0   152.2     .06       0
Bank Sta=133.1,152.2
XS Rating Curve= 0 ,0
Exp/Cntr=0.3,0.1

Type RM Length L Ch R = 1 ,3835.5  ,398.1,398,398.1
XS GIS Cut Line= 2
     1908652.423      347759.531      1908671.52      347578.976
#Sta/Elev= 22
       0 1780.54     9.6 1778.17    19.1 1775.67    28.7 1772.78    38.2 1769.39
    47.8 1765.88    57.3 1763.46    66.9 1762.54    76.4 1761.47      86 1759.52
    95.6 1757.93    98.1  1757.9   105.1 1757.82   113.1 1759.14   114.7  1759.4
   124.2 1762.11   133.8 1764.62   143.3 1766.89   152.9 1769.07   162.4 1771.32
     172 1773.88   181.6  1776.6
#Mann= 3 , 0 , 0
       0      .1       0    95.6    .045       0   113.1     .06       0
Bank Sta=95.6,113.1
XS Rating Curve= 0 ,0
Exp/Cntr=0.3,0.1

Type RM Length L Ch R = 1 ,3437.4  ,341.3,337,332.5
XS GIS Cut Line= 2
     1909043.048      347825.503     1909063.881      347643.212
#Sta/Elev= 23
       0 1769.32     9.7 1766.07    19.3 1762.98      29 1760.58    38.6  1758.6
    48.3 1756.66    57.9 1754.65    67.6 1752.53    77.2 1750.07    86.9 1747.53
    96.6 1746.09    99.3 1746.31   106.2 1746.88  108.731747.786   114.3 1749.78
   115.9 1750.35   125.5 1755.34   135.2 1759.95   144.8 1763.73   154.5 1766.83
   164.2 1769.27   173.8 1771.45   183.5 1773.61
#Mann= 3 , 0 , 0
       0      .1       0    86.9    .045       0  108.73     .06       0
Bank Sta=86.9,108.73
XS Rating Curve= 0 ,0
Exp/Cntr=0.3,0.1

Type RM Length L Ch R = 1 ,3100.4  ,139.3,153,167
XS GIS Cut Line= 3
       1909367.7      347924.462      1909390.27      347882.795
     1909369.436      347651.892
#Sta/Elev= 24
       0 1759.04     9.5 1754.34      19 1749.26    28.4 1744.45    37.9 1740.74
    47.4 1738.39      57 1738.03    76.4 1738.17   134.3 1737.93     144 1737.44
   153.6 1736.25   163.3 1735.36     173 1736.32   182.6 1739.23   192.3  1742.5
     202 1745.17   211.6 1747.26   221.3 1748.69   230.9 1749.31   240.6 1749.24
   250.2 1748.72   259.9 1747.95   269.6 1747.02   279.2 1745.98
#Mann= 3 , 0 , 0
       0      .1       0   153.6    .045       0     173     .06       0
Bank Sta=153.6,173
XS Rating Curve= 0 ,0
Exp/Cntr=0.3,0.1

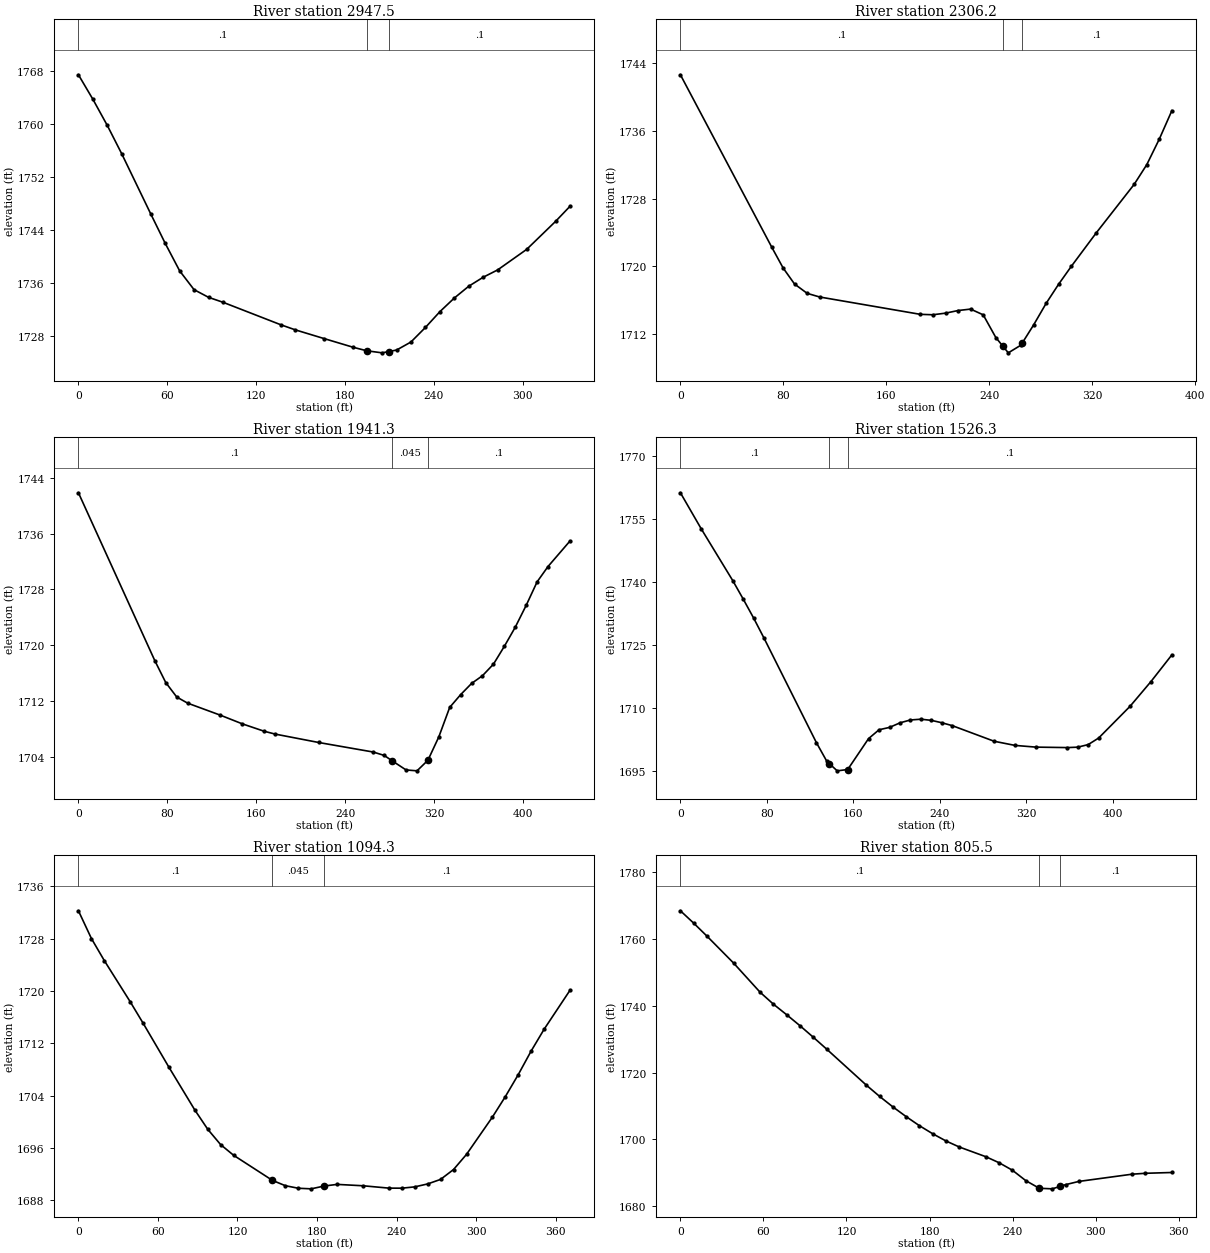
Type RM Length L Ch R = 1 ,2947.5  ,648.4,641.3,633.8
XS GIS Cut Line= 2
     1909418.048      347980.017     1909582.978      347691.823
#Sta/Elev= 28
       0 1767.45     9.8 1763.74    19.5  1759.8    29.3  1755.5    48.8 1746.47
    58.6 1742.01    68.4 1737.84    78.1 1735.01    87.9 1733.85    97.7  1733.1
   136.7 1729.71   146.5 1728.94     166 1727.62   185.6 1726.31   194.8 1725.78
   205.1 1725.47   209.8 1725.67   214.9 1725.89   224.6  1727.1   234.4  1729.3
   244.2 1731.69   253.9 1733.74   263.7 1735.53   273.4 1736.88   283.2 1737.99
   302.8 1741.09   322.3 1745.31     332 1747.58
#Mann= 3 , 0 , 0
       0      .1       0   194.8    .045       0   209.8      .1       0
Bank Sta=194.8,209.8
XS Rating Curve= 0 ,0
Exp/Cntr=0.3,0.1

Type RM Length L Ch R = 1 ,2306.2  ,350.3,364.8,379.3
XS GIS Cut Line= 3
     1909938.881      348368.906     1909996.173      348301.198
     1910058.673       348014.74
#Sta/Elev= 26
       0 1742.65      71 1722.27    79.8 1719.82    88.7 1717.92    98.5 1716.82
   108.2 1716.39   186.4 1714.34   196.2 1714.29     206 1714.48   215.8 1714.79
   225.5 1714.96   235.3 1714.28   245.1  1711.6   250.5 1710.59   254.8 1709.79
   264.6  1710.7   265.5 1710.92   274.4 1713.07   284.2 1715.64   293.9  1717.9
   303.7    1720   323.2 1723.98   352.6  1729.7   362.4 1732.03   372.1 1735.04
   381.9 1738.41
#Mann= 3 , 0 , 0
       0      .1       0   250.5    .045       0   265.5      .1       0
Bank Sta=250.5,265.5
XS Rating Curve= 0 ,0
Exp/Cntr=0.3,0.1

Type RM Length L Ch R = 1 ,1941.3  ,415,415,414.9
XS GIS Cut Line= 2
     1910121.173      348474.809     1910447.561      348176.198
#Sta/Elev= 28
       0 1741.88    68.8 1717.76    78.6 1714.63    88.5 1712.55    98.3 1711.67
   127.8 1709.94   147.5  1708.7   167.1 1707.64     177 1707.23   216.3 1706.02
   265.4 1704.65   275.3 1704.16   282.4 1703.39   294.9 1702.08   304.8 1701.95
   314.6 1703.47   324.4 1706.82   334.2 1711.06   344.1  1712.9   353.9  1714.5
   363.7 1715.61   373.6 1717.27   383.4 1719.83   393.2 1722.57   403.1 1725.73
   412.9 1729.09   422.7 1731.29   442.4 1734.94
#Mann= 3 , 0 , 0
       0      .1       0   282.4    .045       0   314.6      .1       0
Bank Sta=282.4,314.6
XS Rating Curve= 0 ,0
Exp/Cntr=0.3,0.1

Type RM Length L Ch R = 1 ,1526.3  ,424.8,432,445.9
XS GIS Cut Line= 2
     1910392.006      348731.753     1910723.603       348420.99
#Sta/Elev= 30
       0 1761.29    19.3 1752.68    48.4 1740.37      58    1736    67.7 1731.45
    77.4 1726.62   125.7 1701.79   135.4 1697.31   137.8 1696.74     145 1695.04
   154.7 1695.35     174 1702.72   183.7 1704.83   193.4 1705.39   203.1 1706.48
   212.7 1707.16   222.4 1707.34   232.1 1707.07   241.7  1706.5   251.4 1705.81
   290.1 1702.09   309.4  1701.1   328.8 1700.69   357.8 1700.58   367.4 1700.68
   377.1 1701.29   386.8 1702.86   415.8 1710.41   435.1 1716.29   454.5 1722.67
#Mann= 3 , 0 , 0
       0      .1       0   137.8    .045       0   154.7      .1       0
Bank Sta=137.8,154.7
XS Rating Curve= 0 ,0
Exp/Cntr=0.3,0.1

Type RM Length L Ch R = 1 ,1094.3  ,282.1,288.8,288.6
XS GIS Cut Line= 2
     1910668.048      349000.851     1910990.964      348818.559
#Sta/Elev= 30
       0 1732.27     9.8 1728.03    19.5 1724.66      39 1718.38    48.8 1715.08
    68.3 1708.34    87.8 1701.81    97.6 1698.85   107.3 1696.51   117.1 1694.88
   146.4 1691.04   156.1 1690.23   165.9 1689.84   175.6 1689.75   185.4 1690.18
   195.2 1690.43   214.7 1690.22   234.2 1689.86     244 1689.85   253.7 1690.05
   263.5  1690.5   273.2 1691.19     283  1692.7   292.8 1695.02   312.3 1700.71
     322 1703.82   331.8  1707.2   341.5  1710.8   351.3 1714.14   370.8 1720.09
#Mann= 3 , 0 , 0
       0      .1       0   146.4    .045       0   185.4      .1       0
Bank Sta=146.4,185.4
XS Rating Curve= 0 ,0
Exp/Cntr=0.3,0.1

Type RM Length L Ch R = 1 ,805.5   ,173.8,150.2,126.8
XS GIS Cut Line= 2
     1910652.423      349174.462     1911003.117      349118.906
#Sta/Elev= 30
       0  1768.4     9.6  1764.7    19.2 1760.81    38.4 1752.77    57.6 1744.02
    67.2 1740.46    76.8 1737.29    86.4 1734.01      96 1730.57   105.6 1727.04
   134.4 1716.21     144 1712.84   153.5 1709.73   163.1 1706.82   172.7  1704.1
   182.3 1701.69   191.9 1699.53   201.5 1697.73   220.7 1694.82   230.3 1693.01
   239.9 1690.77   249.5 1687.68   259.3 1685.38   268.7 1685.21   274.3 1685.94
   278.3 1686.46   287.9 1687.43   326.3 1689.59   335.9 1689.86   355.1  1690.1
#Mann= 3 , 0 , 0
       0      .1       0   259.3    .045       0   274.3      .1       0
Bank Sta=259.3,274.3
XS Rating Curve= 0 ,0
Exp/Cntr=0.3,0.1

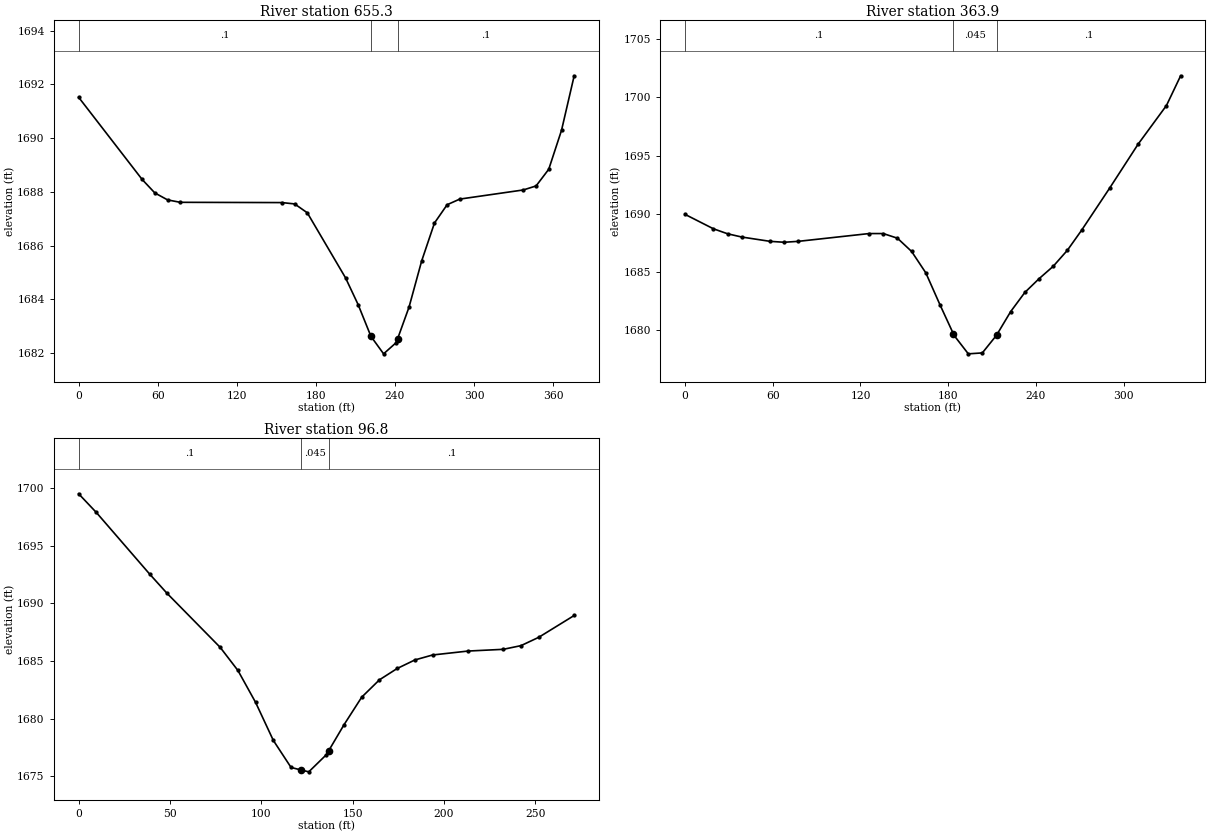
Type RM Length L Ch R = 1 ,655.3   ,278.3,291.4,303.4
XS GIS Cut Line= 2
     1910945.825      349419.688     1911089.055      349072.031
#Sta/Elev= 24
       0 1691.52    48.2 1688.46    57.8 1687.96    67.5  1687.7    77.1 1687.61
   154.3  1687.6   163.9 1687.55   173.5 1687.22   202.5  1684.8   212.1  1683.8
   221.8 1682.62   231.4 1681.97     241 1682.39   242.1 1682.54   250.7 1683.71
   260.3 1685.43     270 1686.84   279.6 1687.52   289.2 1687.73   337.4 1688.07
   347.1 1688.22   356.7 1688.84   366.4 1690.29     376 1692.32
#Mann= 3 , 0 , 0
       0      .1       0   221.8    .045       0   242.1      .1       0
Bank Sta=221.8,242.1
XS Rating Curve= 0 ,0
Exp/Cntr=0.3,0.1

Type RM Length L Ch R = 1 ,363.9   ,291,267.1,242.8
XS GIS Cut Line= 2
     1911069.523      349512.135     1911342.961      349311.615
#Sta/Elev= 28
       0 1689.93    19.4 1688.69    29.1 1688.26    38.8 1687.98    58.1 1687.61
    67.8 1687.53    77.5 1687.61   125.9 1688.28   135.6 1688.28   145.3 1687.88
     155 1686.74   164.7  1684.9   174.4 1682.15   183.6 1679.64   184.1  1679.5
   193.8 1677.92   203.4    1678   213.1 1679.52   222.8 1681.56   232.5 1683.21
   242.2 1684.39   251.9 1685.46   261.6 1686.84   271.3 1688.56   290.6 1692.21
     310 1695.98   329.4 1699.31   339.1 1701.87
#Mann= 3 , 0 , 0
       0      .1       0   183.6    .045       0   213.1      .1       0
Bank Sta=183.6,213.1
XS Rating Curve= 0 ,0
Exp/Cntr=0.3,0.1

Type RM Length L Ch R = 1 ,96.8    ,117.1,96.8,75.7
XS GIS Cut Line= 2
     1911389.604      349693.023     1911368.568      349422.564
#Sta/Elev= 24
       0 1699.48     9.7 1697.86    38.8 1692.54    48.4 1690.86    77.5 1686.18
    87.2 1684.18    96.9 1681.41   106.6 1678.12   116.3 1675.78   121.8 1675.56
     126  1675.4   135.6 1676.88   136.8  1677.2   145.3 1679.48     155 1681.87
   164.7 1683.37   174.4 1684.35   184.1 1685.09   193.8 1685.52   213.2 1685.86
   232.5 1686.01   242.2 1686.33   251.9 1687.05   271.3 1688.94
#Mann= 3 , 0 , 0
       0      .1       0   121.8    .045       0   136.8      .1       0
Bank Sta=121.8,136.8
XS Rating Curve= 0 ,0
Exp/Cntr=0.3,0.1

Chan Stop Cuts=-1
Use User Specified Reach Order=0
Composite Channel Slope=5